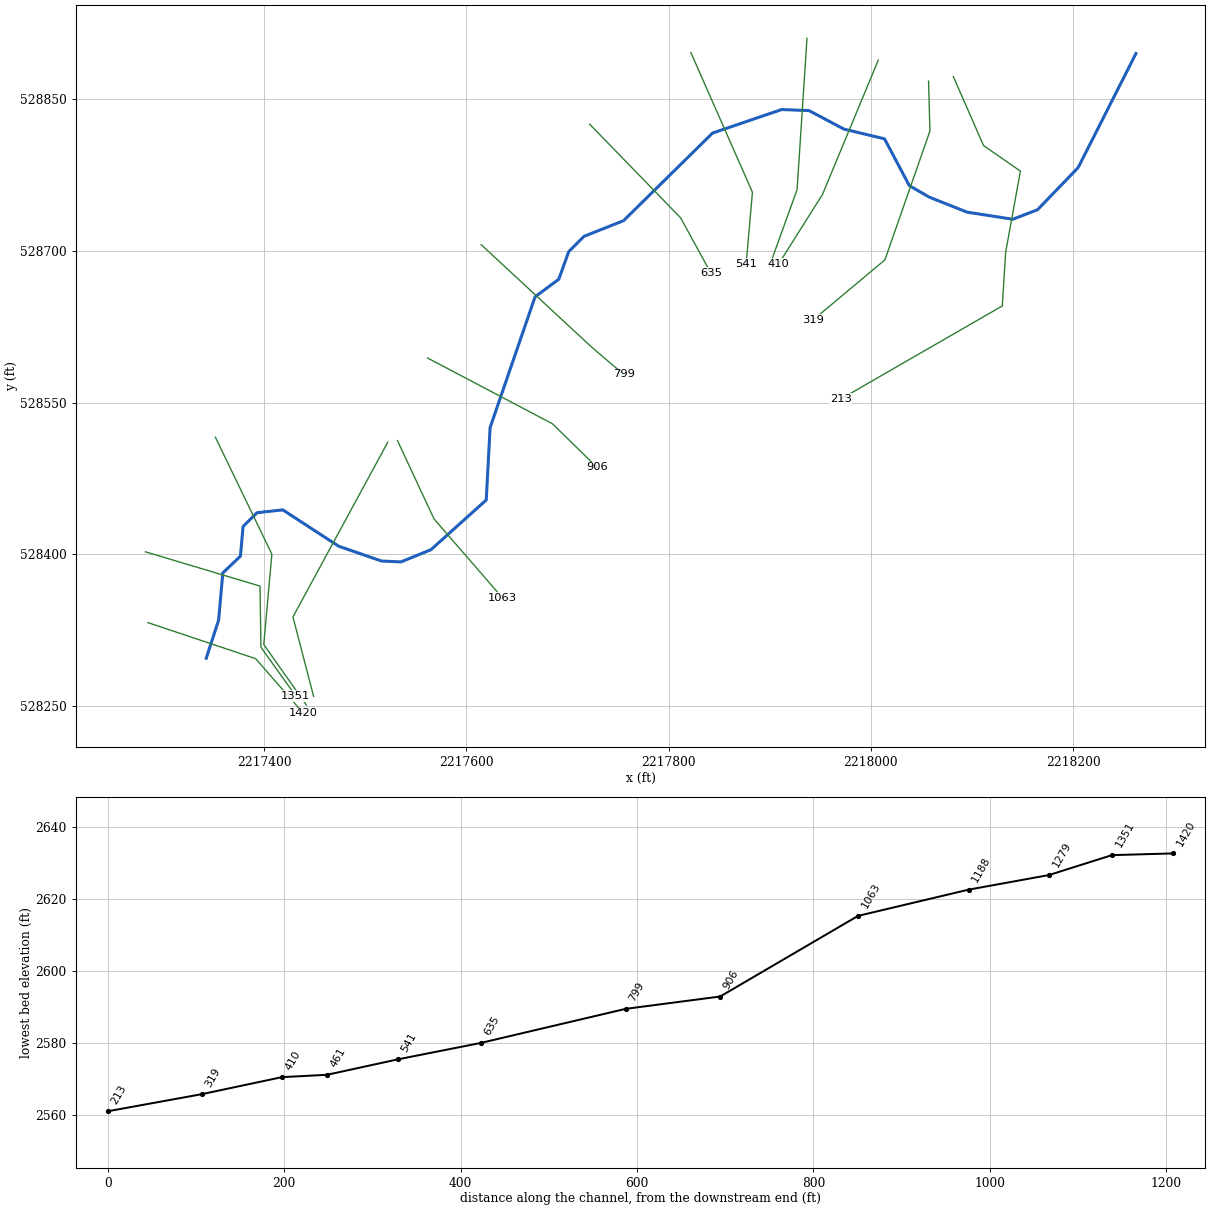
--- BIGRN2.prj (project) ---

Proj Title=BIGRN2
Current Plan=p01
Default Exp/Contr=0,0
English Units
Geom File=g01
Flow File=f01
Plan File=p01
Background Map Layer=Inundation Boundary (10pct Value_0)
BEGIN DESCRIPTION:
----------MODEL BY WOOD PLC 2021----------
Stream Name: Big Run II
Flood Zone: Enhanced Approximate
Pocahontas County, WV
HEC-RAS Version: RAS 6.1
Vertical Datum: NAVD88
Projection: NAD 1983 StatePlane West Virginia S FIPS 4702 (US Feet)
Terrain: 1-meter LIDAR (FEMA Region III 3DEP collected 2016-2018)
Land Use: 2019 NLCD
Hydrologic Method:
WV SIR2010-5033 regression equations
Model Notes:
END DESCRIPTION:
DSS Export Rating Curves= 0
DSS Export Rating Curve Sorted= 0
DSS Export Volume Flow Curves= 0
DXF OffsetX= 0
DXF OffsetY= 0
DXF ScaleX= 0
DXF ScaleY= 0

--- BIGRN2.p01 (plan) ---

Plan Title=Floodplain
Program Version=6.10
Short Identifier=Floodplain
Geom File=g01
Flow File=f01
Subcritical Flow
K Sum by GR= 0
Std Step Tol= 0.01
Critical Tol= 0.01
Num of Std Step Trials= 20
Max Error Tol= 0.3
Flow Tol Ratio= 0.001
Split Flow NTrial= 30
Split Flow Tol= 0.02
Split Flow Ratio= 0.02
Log Output Level= 0
Friction Slope Method= 1
Unsteady Friction Slope Method= 2
Unsteady Bridges Friction Slope Method= 1
Parabolic Critical Depth
Global Vel Dist= 0 , 0 , 0
Global Log Level= 0
CheckData=True
Encroach Param=-1 ,0,0, 0
Mapping Interval=1HOUR
Computation Time Step Use Courant=        0
Computation Time Step Use Time Series=    0
Computation Time Step Count To Double=0
Computation Time Step Max Doubling=0
Computation Time Step Max Halving=0
Computation Time Step Residence Courant=0
Run HTab= 0
Run UNet= 0
Run Sediment= 0
Run PostProcess= 0
Run WQNet= 0
Run RASMapper=-1
UNET Theta= 0
UNET Theta Warmup= 0
UNET ZTol= 0
UNET ZSATol= 0
UNET MxIter= 0
UNET Max Iter WO Improvement= 0
UNET MaxInSteps= 0
UNET DtIC= 0
UNET DtMin= 0
UNET MaxCRTS= 0
UNET WFStab= 0
UNET SFStab= 0
UNET WFX= 1
UNET SFX= 1
UNET Gravity=32.174
UNET 1D Methodology=Finite Difference
UNET DSS MLevel= 1
UNET Pardiso=0
UNET DZMax Abort= 0
UNET Use Existing IB Tables= 0
UNET Froude Reduction=False
UNET Froude Limit= 0
UNET Froude Power= 0
UNET D1 Cores= 0
UNET WindReference=Eulerian
UNET WindDragFormulation=Hsu (1988)
UNET D2 Coriolis=0
UNET D2 Cores= 0
UNET D2 Theta= 1
UNET D2 Theta Warmup= 1
UNET D2 Z Tol= 0.01
UNET D2 Volume Tol= 0.01
UNET D2 Max Iterations= 20
UNET D2 Equation= 0
UNET D2 RampUpFraction=0.1
UNET D2 TimeSlices= 1
UNET D2 Turbulence Formulation=Non-Conservative (original)
UNET D2 Eddy Viscosity=0.3
UNET D2 Transverse Eddy Viscosity=0.1
UNET D2 Smagorinsky Mixing=0
UNET D2 BCVolumeCheck=0
UNET D2 Cores=0
UNET D2 SolverType=PARDISO (Direct)
UNET D2 Minimum Iterations= 2147483647
UNET D2 Maximum Iterations= 2147483647
UNET D2 Restart Number= 10
UNET D2 Relaxation Coeff=1.3
UNET D2 SOR Precondition Iterations= 10
UNET D2 ILUT Maximum Fill= 8
UNET D2 ILUT Tolerance=1E-08
UNET D1D2 MaxIter= 0
UNET D1D2 ZTol=0.01
UNET D1D2 QTol=0.1
UNET D1D2 MinQTol=1
Write IC File= 0
Write IC File at Fixed DateTime=0
Write IC File at Sim End=0
Echo Input=False
Echo Parameters=False
Echo Output=False
Write Detailed= 0
HDF Write Warmup=0
HDF Write Time Slices=0
HDF Flush=0
HDF Compression= 1
HDF Chunk Size= 1
HDF Spatial Parts= 1
HDF Use Max Rows=0
HDF Fixed Rows= 1
Calibration Method= 0
Calibration Iterations= 20
Calibration Max Change=0.05
Calibration Tolerance=0.2
Calibration Maximum=1.5
Calibration Minimum=0.5
Calibration Optimization Method= 1
WQ AD Non Conservative
WQ ULTIMATE=-1
WQ Max Comp Step=1HOUR
WQ Output Interval=15MIN
WQ Output Selected Increments= 0
WQ Output face flow=0
WQ Output face velocity=0
WQ Output face area=0
WQ Output face dispersion=0
WQ Output cell volume=0
WQ Output cell surface area=0
WQ Output cell continuity=0
WQ Output cumulative cell continuity=0
WQ Output face conc=0
WQ Output face dconc_dx=0
WQ Output face courant=0
WQ Output face peclet=0
WQ Output face adv mass=0
WQ Output face disp mass=0
WQ Output cell mass=0
WQ Output cell source sink temp=0
WQ Output nsm pathways=0
WQ Output nsm derived pathways=0
WQ Create Restart=0
WQ Fixed Restart=0
WQ System Summary=0
WQ Write To DSS=0
Sorting and Armoring Iterations= 10
XS Update Threshold= 0.02
Bed Roughness Predictor= 0
Hydraulics Update Threshold= 0.02
Energy Slope Method= 1
Volume Change Method= 1
Sediment Retention Method= 0
Sediment TS Multiplier= 1
Warm Up Method= 0
XS Weighting Method= 0
Number of US Weighted Cross Sections= 1
Number of DS Weighted Cross Sections= 1
Upstream XS Weight=0
Main XS Weight=1
Downstream XS Weight=0
Number of DS XS's Weighted with US Boundary= 1
Upstream Boundary Weight= 1
Weight of XSs Associated with US Boundary= 0
Number of US XS's Weighted with DS Boundary= 1
Downstream Boundary Weight= 0.5
Weight of XSs Associated with DS Boundary= 0.5
Percentile Method= 0
Sediment Output Level= 3
Mass or Volume Output= 0
Output Increment Type= 1
Profile and TS Output Increment= 1
Transport Output Increment 1
XS Output Flag= 0
XS Output Increment= 10
Read HDF5 Sediment Hotstart= 0
Sediment Hotstart Type= 0
Write Gradation File= 0
Read Gradation Hotstart= 0
Write HDF5 File= 1
Write Binary Output= 1
Write DSS Sediment File= 0
DSS Sediment Output Type= 1
SV Curve= 0
Specific Gage Flag= 0
Subcell Erosion Methods= 0
Subcell Deposition Methods= 0
Advection Scheme= 1
Matrix Solver= 0
Implicit Weighting Factor= 1
Maximum Outer Loop Convergence Iterations= 5
Convergence Maximum Absolute= 0.001
Convergence RMSE= 0.0001
Grain Fractions Max Abs Error= 0.001
Max Subgrid Regions= 1
Max Subgrid Length Scale= 3.402823E+38
Initial Layer Thickness= 3.402823E+38
Min Layer Thickness= 3.402823E+38
Max Layer Thickness= 3.402823E+38
Number of Layers= 5

--- BIGRN2.f01 (steady flow) ---

Flow Title=Flow
Program Version=6.00
Number of Profiles= 6
Profile Names=01pct,10pct,04pct,02pct,0_2pct,01plus
River Rch & RM=BIGRN2,Main            ,1420
     550     290     386     465     768     813
Boundary for River Rch & Prof#=BIGRN2,Main            , 1
Up Type= 0
Dn Type= 3
Dn Slope=0.03838
Boundary for River Rch & Prof#=BIGRN2,Main            , 2
Up Type= 0
Dn Type= 3
Dn Slope=0.03838
Boundary for River Rch & Prof#=BIGRN2,Main            , 3
Up Type= 0
Dn Type= 3
Dn Slope=0.03838
Boundary for River Rch & Prof#=BIGRN2,Main            , 4
Up Type= 0
Dn Type= 3
Dn Slope=0.03838
Boundary for River Rch & Prof#=BIGRN2,Main            , 5
Up Type= 0
Dn Type= 3
Dn Slope=0.03838
Boundary for River Rch & Prof#=BIGRN2,Main            , 6
Up Type= 0
Dn Type= 3
Dn Slope=0.03838
DSS Import GetInterval= 0
DSS Import GetPeak= 0
DSS Import FillOption= 0

--- BIGRN2.g01 (geometry) ---

Geom Title=Geometry
Program Version=6.10

River Reach=BIGRN2          ,Main
Reach XY= 30
     2217342.822      528297.4242217355.06129377528335.165112443
2217359.20173733528381.7451024762217376.62610397528398.306876711
 2217379.2138812528427.6350185842217393.01535973 528441.26397863
2217418.51745545528444.0790234982217473.75400912528408.140430162
2217516.02621267528393.5263895852217535.34310705528392.613766818
2217565.01628589 528404.690060532217619.70464456528453.857827788
2217623.50005115528525.4529976542217667.95292775528654.718045908
2217691.41544125528672.1424125512217701.30588636528699.524145594
2217716.31499426528714.5332534932217755.47668958528730.059916838
 2217843.4611152528816.6641946042217911.77843391 528839.95418962
2217938.86383553528838.9190787312217973.36753185 528820.63211968
2218013.56433806 528810.971084712218038.06196245 528764.73613164
2218057.72906935528753.349911854     2218095.178      528738.485
     2218140.384      528731.466     2218164.861      528740.868
     2218204.993      528782.512     2218262.151      528895.305

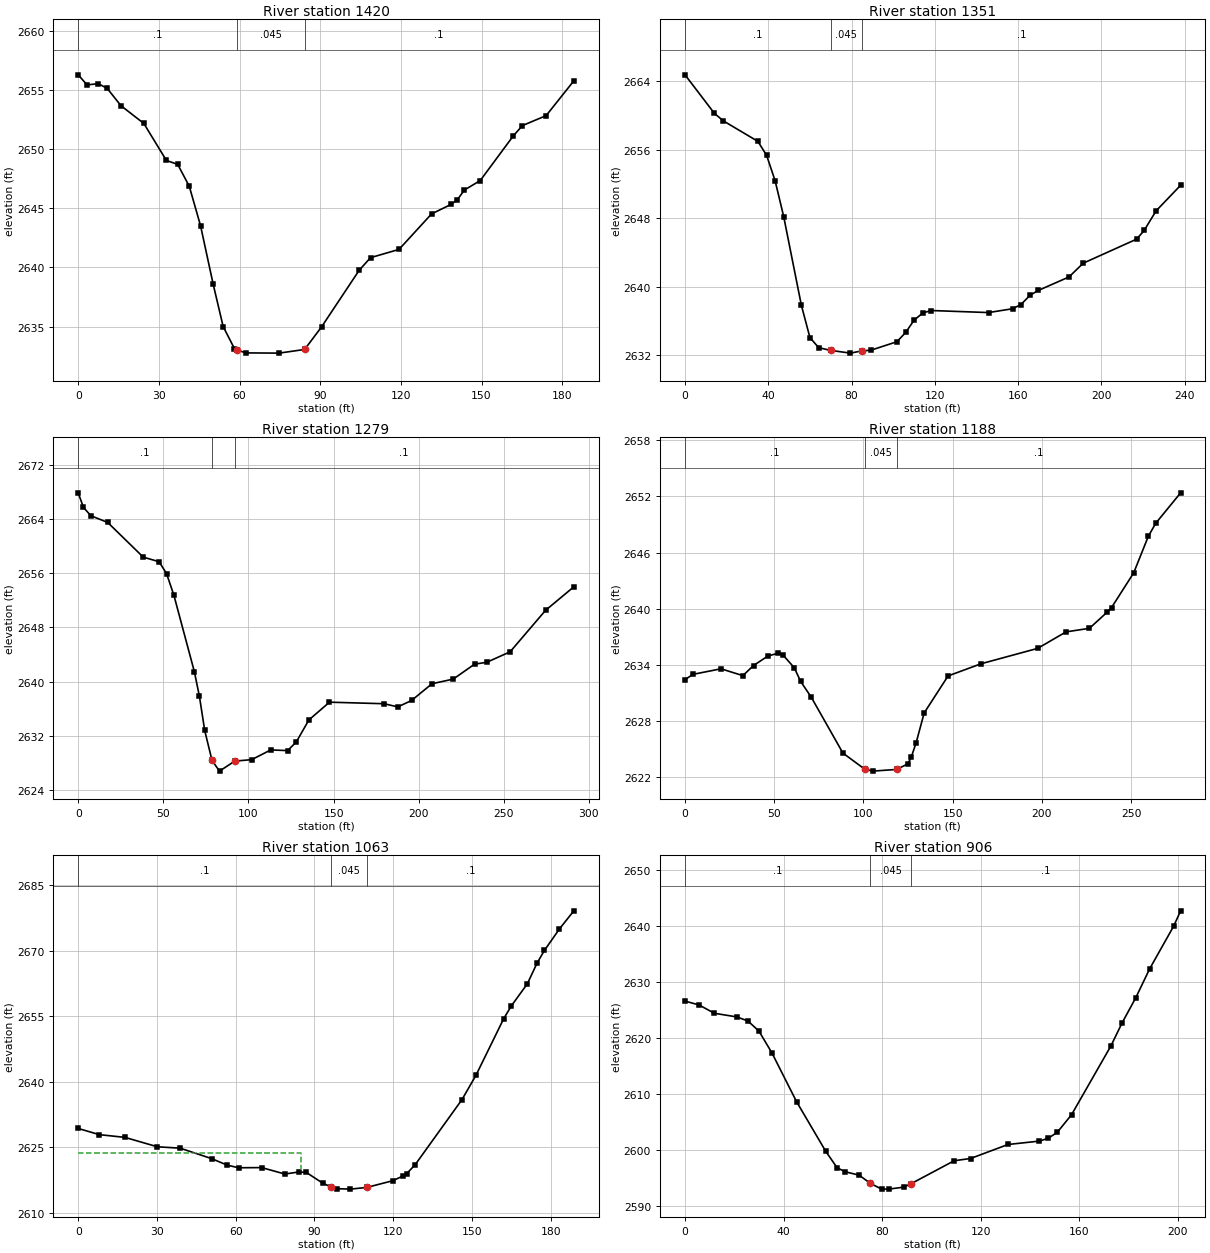
Type RM Length L Ch R = 1 ,1420    ,69.7,69.7,69.7
XS GIS Cut Line= 3
2217285.05394969528332.6043969922217391.65885487 528296.93583849
2217438.94975266528242.831845257
#Sta/Elev= 30
       0 2656.28     3.3 2655.43     7.5 2655.53    10.8 2655.13    15.9 2653.67
    24.4 2652.17    32.8 2649.04      37 2648.71    41.3 2646.86    45.5 2643.52
    50.2 2638.57    53.9    2635    58.1 2633.13    58.9 2633.03    62.3 2632.77
    74.7 2632.75    84.2 2633.06    90.5 2634.97   104.5 2639.76   108.7 2640.82
   119.3 2641.52   131.4 2644.52   138.7 2645.33     141 2645.72   143.6 2646.54
   149.5 2647.34   161.8 2651.12   165.2 2651.99     174 2652.83   184.3 2655.77
#Mann= 3 ,-1,0
       0      .1       0    58.9    .045       0    84.2      .1       0
Bank Sta=58.9,84.2
XS Rating Curve= 0 ,0
Exp/Cntr(USF)=0,0
Exp/Cntr=0.3,0.1

Type RM Length L Ch R = 1 ,1351    ,80.8,71.5,59.9
XS GIS Cut Line= 4
2217282.64478346528402.5824489722217396.00347008528368.691707611
2217396.87995477528308.2142639752217431.35501926528260.007606004
#Sta/Elev= 30
       0 2664.73    14.1 2660.24    18.4 2659.36      35 2656.97    39.2 2655.34
    43.3 2652.36    47.4  2648.2    55.9 2637.85      60 2634.09    64.2 2632.91
    69.9 2632.59    79.5 2632.27    85.1 2632.54    89.3 2632.61   101.8  2633.6
     106 2634.68   110.1 2636.13   114.3 2636.96   118.3 2637.24   145.8    2637
   157.4 2637.45   161.4 2637.94   165.8 2639.03   169.8 2639.59   184.5 2641.16
   191.3 2642.76     217 2645.57   220.6 2646.59   226.3 2648.86   238.1 2651.85
#Mann= 3 ,-1,0
       0      .1       0    69.9    .045       0    85.1      .1       0
Bank Sta=69.9,85.1
XS Rating Curve= 0 ,0
Exp/Cntr(USF)=0,0
Exp/Cntr=0.3,0.1

Type RM Length L Ch R = 1 ,1279    ,103,91.1,80.3
XS GIS Cut Line= 4
2217351.87101198528515.9263513432217407.68993262528400.245156464
2217399.67426128528310.962799699 2217441.7551449528251.248021983
#Sta/Elev= 30
       0 2667.94     3.1 2665.77     7.5 2664.54    17.3 2663.56    38.2 2658.42
    47.5 2657.74    51.9 2655.98    56.2 2652.78    68.2 2641.48    71.2 2637.81
    74.3 2632.75    78.6 2628.31      83 2626.73    91.9 2628.21   101.9 2628.43
   113.1 2629.87     123 2629.77   128.1 2631.05   135.5 2634.31   147.6 2636.94
   179.7 2636.71   187.7 2636.24   195.8 2637.19   207.8 2639.67   220.3 2640.36
   232.8 2642.57     240 2642.85   253.7  2644.4   274.5 2650.54   291.1 2654.02
#Mann= 3 ,-1,0
       0      .1       0    78.6    .045       0    91.9      .1       0
Bank Sta=78.6,91.9
XS Rating Curve= 0 ,0
Exp/Cntr=0.3,0.1

Type RM Length L Ch R = 1 ,1188    ,101.4,125.3,143.4
XS GIS Cut Line= 3
2217522.30997927  528510.94718952217428.52972434528338.215181475
2217448.96901067528259.664198708
#Sta/Elev= 30
       0 2632.44     4.5    2633    20.2 2633.59    32.4 2632.86    38.4 2633.94
    46.4 2634.95    52.1 2635.25    54.8 2635.08    61.2 2633.71    64.8 2632.24
    70.7 2630.57    88.5 2624.59   100.7 2622.88   105.1 2622.67   118.6 2622.85
   124.9 2623.45   126.8 2624.18   129.5  2625.7     134 2628.88   147.4 2632.83
   165.9 2634.13   197.6 2635.77   213.5 2637.53   226.6 2637.91   236.5 2639.63
     239 2640.13   251.4 2643.83   259.6 2647.73   263.7 2649.11   277.7 2652.37
#Mann= 3 ,-1,0
       0      .1       0   100.7    .045       0   118.6      .1       0
Bank Sta=100.7,118.6
XS Rating Curve= 0 ,0
Exp/Cntr(USF)=0,0
Exp/Cntr=0.3,0.1

Type RM Length L Ch R = 1 ,1063    ,147.4,156.3,162.6
XS GIS Cut Line= 3
2217531.92846696528512.5502707812217567.99779578528435.201598974
 2217635.7279799528357.051386527
#Sta/Elev= 30
       0 2629.27     8.1 2627.85    17.8 2627.23    30.2 2625.07    38.8 2624.76
    50.9 2622.35    56.7 2620.88    61.1 2620.27    69.9 2620.31    78.7 2618.84
      84  2619.3    86.9  2619.2    93.3 2616.69   96.44 2615.87    98.6 2615.48
   103.7 2615.38     110 2615.78   119.8  2617.3   123.8 2618.41   125.1  2618.9
   128.4    2621   146.2 2635.88   151.5 2641.42   162.1 2654.42     165 2657.33
   171.1  2662.4   174.8 2667.14   177.6 2670.03   183.3 2674.94   188.8  2679.1
#Mann= 3 ,-1,0
       0      .1       0   96.44    .045       0     110      .1       0
#XS Ineff= 2 , 0
           84.85 2623.72
Permanent Ineff=
       F       F
Bank Sta=96.44,110
XS Rating Curve= 0 ,0
Exp/Cntr(USF)=0,0
Exp/Cntr=0.3,0.1

Type RM Length L Ch R = 1 ,906     ,117.1,107.1,100.3
XS GIS Cut Line= 3
2217561.60923367528594.2883938382217685.15978619528529.223737394
 2217729.1950436528486.178036331
#Sta/Elev= 30
       0 2626.62     5.7 2625.93    11.9 2624.44      21 2623.79    25.5 2623.07
      30 2621.26    35.3 2617.33    45.3  2608.6    57.1 2599.75    61.7 2596.81
    64.9 2596.08    70.7 2595.46    75.2    2594    79.8 2592.97    82.7 2592.96
    88.8 2593.32    91.6 2593.89   109.3 2598.05   115.9 2598.44   131.1 2600.95
   143.9 2601.56   147.5 2602.08   151.1 2603.12   156.9 2606.27   172.9  2618.6
   177.4 2622.69     183 2627.23   188.6 2632.38   198.4 2640.06   201.2 2642.78
#Mann= 3 ,-1,0
       0      .1       0    75.2    .045       0    91.6      .1       0
Bank Sta=75.2,91.6
XS Rating Curve= 0 ,0
Exp/Cntr=0.3,0.1

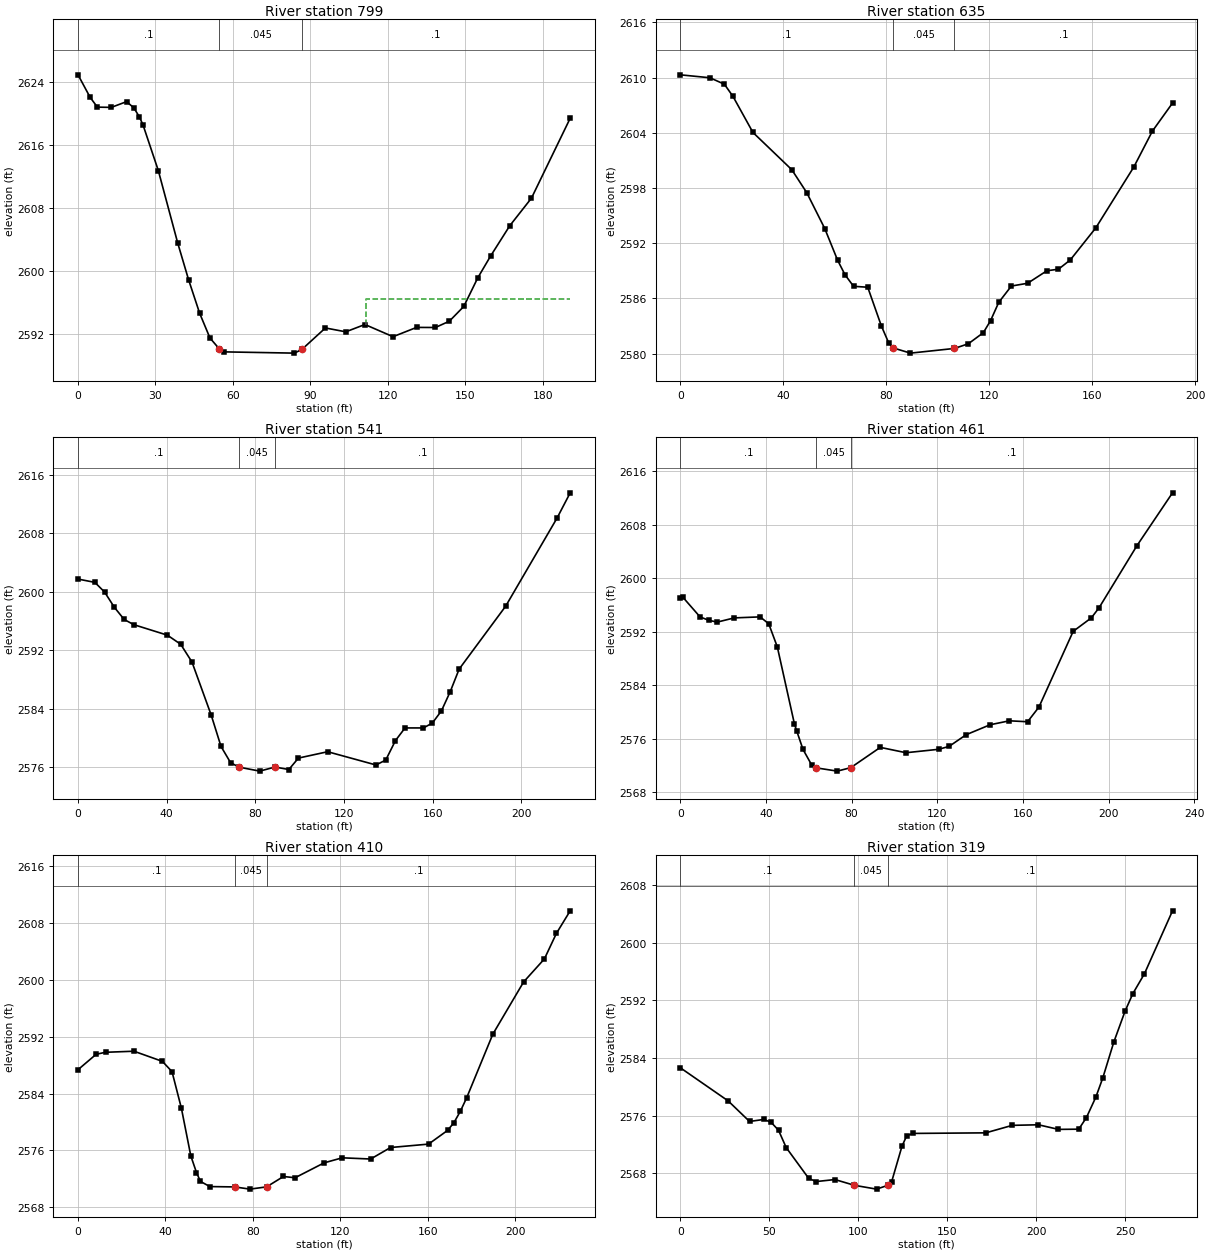
Type RM Length L Ch R = 1 ,799     ,163.7,164.1,159.8
XS GIS Cut Line= 3
2217614.71077621528706.3024508342217724.22126622528604.738835507
2217755.62162081528578.004248985
#Sta/Elev= 30
       0 2624.92     4.7 2622.05     7.5 2620.81    12.9 2620.78    18.8 2621.51
    21.6 2620.73    23.8 2619.55    25.2 2618.52    31.1 2612.74    38.6 2603.54
    42.8 2598.88    47.1  2594.6    51.1 2591.45    54.6 2590.11    56.6 2589.69
    83.8 2589.53    86.7    2590    95.8 2592.73   103.7 2592.24   111.1 2593.17
     122 2591.62   131.1  2592.8   138.4 2592.79   143.8 2593.59   149.4 2595.47
   154.8  2599.1   159.8 2601.89   167.2 2605.73   175.6 2609.24   190.6  2619.4
#Mann= 3 ,-1,0
       0      .1       0    54.6    .045       0    86.7      .1       0
#XS Ineff= 2 , 0
                          111.44         2596.41
Permanent Ineff=
       F       F
Bank Sta=54.6,86.7
XS Rating Curve= 0 ,0
Exp/Cntr(USF)=0,0
Exp/Cntr=0.3,0.1

Type RM Length L Ch R = 1 ,635     ,98.8,94.2,85.8
XS GIS Cut Line= 3
2217721.98790682528825.4251052622217811.90963247528732.876082394
2217841.76034352528678.337944729
#Sta/Elev= 30
       0  2610.3    11.5 2609.98    17.1 2609.28    20.4 2607.98    28.2 2604.04
    43.3 2599.99    49.1  2597.5    56.1  2593.6    61.1 2590.15      64 2588.56
    67.3 2587.32    72.8 2587.22    78.1 2583.01    80.9  2581.2   82.73 2580.62
    89.4 2580.06   106.5 2580.57   111.9 2581.08   117.7 2582.28   120.5 2583.58
   123.7 2585.58   128.6 2587.35   134.9 2587.65   142.4 2589.01   146.9 2589.18
   151.5 2590.19   161.4 2593.67   176.2  2600.3   183.4 2604.19   191.2 2607.23
#Mann= 3 ,-1,0
       0      .1       0   82.73    .045       0   106.5      .1       0
Bank Sta=82.73,106.5
XS Rating Curve= 0 ,0
Exp/Cntr(USF)=0,0
Exp/Cntr=0.3,0.1

Type RM Length L Ch R = 1 ,541     ,87.2,80.4,72.2
XS GIS Cut Line= 3
2217822.08774708528896.1756409022217882.91147194528758.195894708
2217876.71646292 528687.23488238
#Sta/Elev= 30
       0 2601.72     7.6 2601.27      12 2599.94    16.4 2597.86    20.8 2596.21
    25.1  2595.5    40.3 2594.06    46.3 2592.82    51.4 2590.39    60.1 2583.12
    64.5 2578.86    68.8 2576.65    72.62576.033      82 2575.49    88.8 2576.05
    95.1 2575.71    99.4 2577.27   112.6 2578.14   134.4 2576.33   138.8    2577
   143.2 2579.67   147.5 2581.39   155.8 2581.39   159.8 2582.05   163.9 2583.71
   167.9 2586.35   171.9 2589.42   192.9 2598.02   216.1 2610.07     222  2613.5
#Mann= 3 ,-1,0
       0      .1       0    72.6    .045       0    88.8      .1       0
Bank Sta=72.6,88.8
XS Rating Curve= 0 ,0
Exp/Cntr(USF)=0,0
Exp/Cntr=0.3,0.1

Type RM Length L Ch R = 1 ,461     ,55.5,51,45.7
XS GIS Cut Line= 3
2217936.87204652528910.3661481362217927.07543869528760.745228578
2217899.91211699528685.489468444
#Sta/Elev= 30
       0 2597.08     1.2 2597.17     9.2 2594.24    13.2 2593.74    17.2 2593.46
    25.2 2594.09    37.3 2594.24    41.3  2593.2    45.3 2589.75    53.3 2578.23
    54.4 2577.16    57.3 2574.43    61.3 2572.14   63.45 2571.68    73.3 2571.19
   79.62 2571.71    93.4 2574.74   105.4 2573.94   120.6 2574.45   125.5 2574.88
   133.5 2576.63   144.7 2578.12   153.7 2578.71   162.2 2578.57   167.5 2580.76
   183.5 2592.08     192  2594.1   195.6 2595.61   213.3 2604.89   229.9 2612.78
#Mann= 3 ,-1,0
       0      .1       0   63.45    .045       0   79.62      .1       0
Bank Sta=63.45,79.62
XS Rating Curve= 0 ,0
Exp/Cntr(USF)=0,0
Exp/Cntr=0.3,0.1

Type RM Length L Ch R = 1 ,410     ,86,91.1,91.1
XS GIS Cut Line= 3
2218007.37483483528888.8542666142217952.18293635528755.943164158
2217908.81787326 528687.23488238
#Sta/Elev= 30
       0 2587.36     8.3 2589.53    12.6 2589.81    25.6 2589.96    38.6 2588.53
      43 2587.09    47.3 2581.93    51.6 2575.23    54.2 2572.88      56 2571.63
    60.3  2570.9   71.67 2570.85    78.7 2570.54    86.3 2570.86      94 2572.32
    99.3 2572.14   112.6 2574.24   120.9 2574.95   133.9 2574.78     143  2576.4
   160.4 2576.88   169.1 2578.81     172  2579.9   174.9 2581.48   177.8 2583.38
   189.8 2592.36   203.9 2599.72   213.4 2602.96   218.9 2606.56   225.2 2609.73
#Mann= 3 ,-1,0
       0      .1       0   71.67    .045       0    86.3      .1       0
Bank Sta=71.67,86.3
XS Rating Curve= 0 ,0
Exp/Cntr(USF)=0,0
Exp/Cntr=0.3,0.1

Type RM Length L Ch R = 1 ,319     ,104.2,106.3,108.6
XS GIS Cut Line= 4
2218057.10314259528868.0626143332218058.43904366528818.634274836
2218013.90900808 528691.27837307 2217943.1062515528632.053425745
#Sta/Elev= 30
       0 2582.64    26.9 2578.04    38.9 2575.19    46.9 2575.47      51 2575.08
    55.2 2573.97    59.5 2571.57    72.2 2567.28    76.4 2566.85    86.9 2567.13
   97.88 2566.33   110.3  2565.8   116.9 2566.35   118.8 2566.83   124.6 2571.75
   127.3 2573.22   130.9 2573.53   171.7 2573.61   186.6 2574.65   201.3 2574.73
   212.6 2574.09     224 2574.12   228.3 2575.73   233.6 2578.57   237.5 2581.23
   243.7 2586.21     250 2590.48   254.4 2592.93   260.9 2595.68   276.7 2604.42
#Mann= 3 ,-1,0
       0      .1       0   97.88    .045       0   116.9      .1       0
Bank Sta=97.88,116.9
XS Rating Curve= 0 ,0
Exp/Cntr(USF)=0,0
Exp/Cntr=0.3,0.1

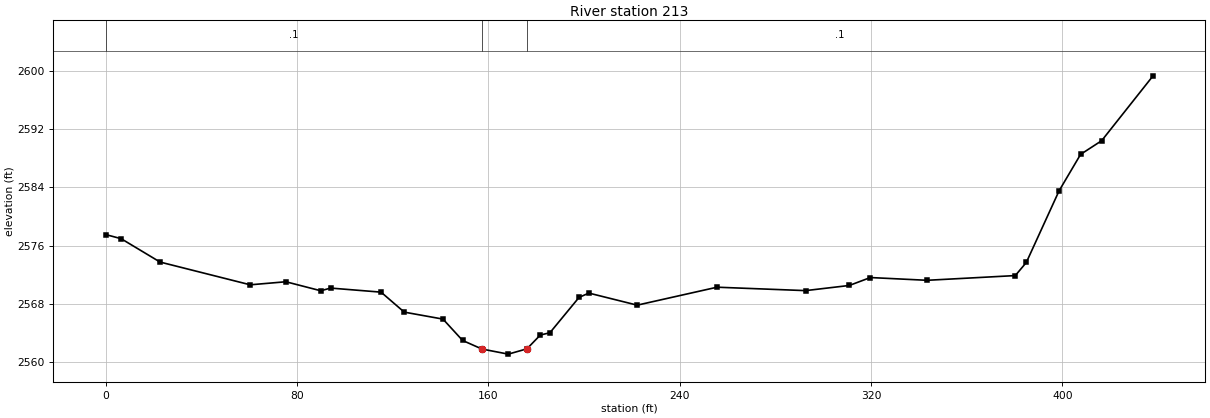
Type RM Length L Ch R = 1 ,213     ,,,
XS GIS Cut Line= 6
2218081.59466217528872.5156178912218111.42978601528804.384663449
2218147.91037082528779.0518696732218133.32596286528698.761669567
 2218130.0184658528645.7472817082217970.26957321 528553.68056312
#Sta/Elev= 30
       0 2577.51     6.4 2576.95    22.7 2573.73    60.4  2570.6    75.3 2571.02
    89.9 2569.78      94 2570.15   115.1 2569.59   124.8 2566.84     141 2565.88
   149.2 2562.94   157.3 2561.76   168.3 2561.06   176.1 2561.79   181.7 2563.69
   185.7    2564   197.9 2568.87     202 2569.46   222.2  2567.8   255.6 2570.27
   292.6  2569.8   310.9 2570.51   319.7  2571.6   343.4 2571.22   380.3 2571.87
   384.9 2573.67   398.6 2583.53   407.6 2588.55   416.4 2590.43   437.9 2599.36
#Mann= 3 ,0,0
       0      .1       0   157.3    .045       0   176.1      .1       0
Bank Sta=157.3,176.1
XS Rating Curve= 0 ,0
Exp/Cntr(USF)=0,0
Exp/Cntr=0.3,0.1
LCMann Table=0

Chan Stop Cuts=-1
Use User Specified Reach Order=0
Composite Channel Slope=5